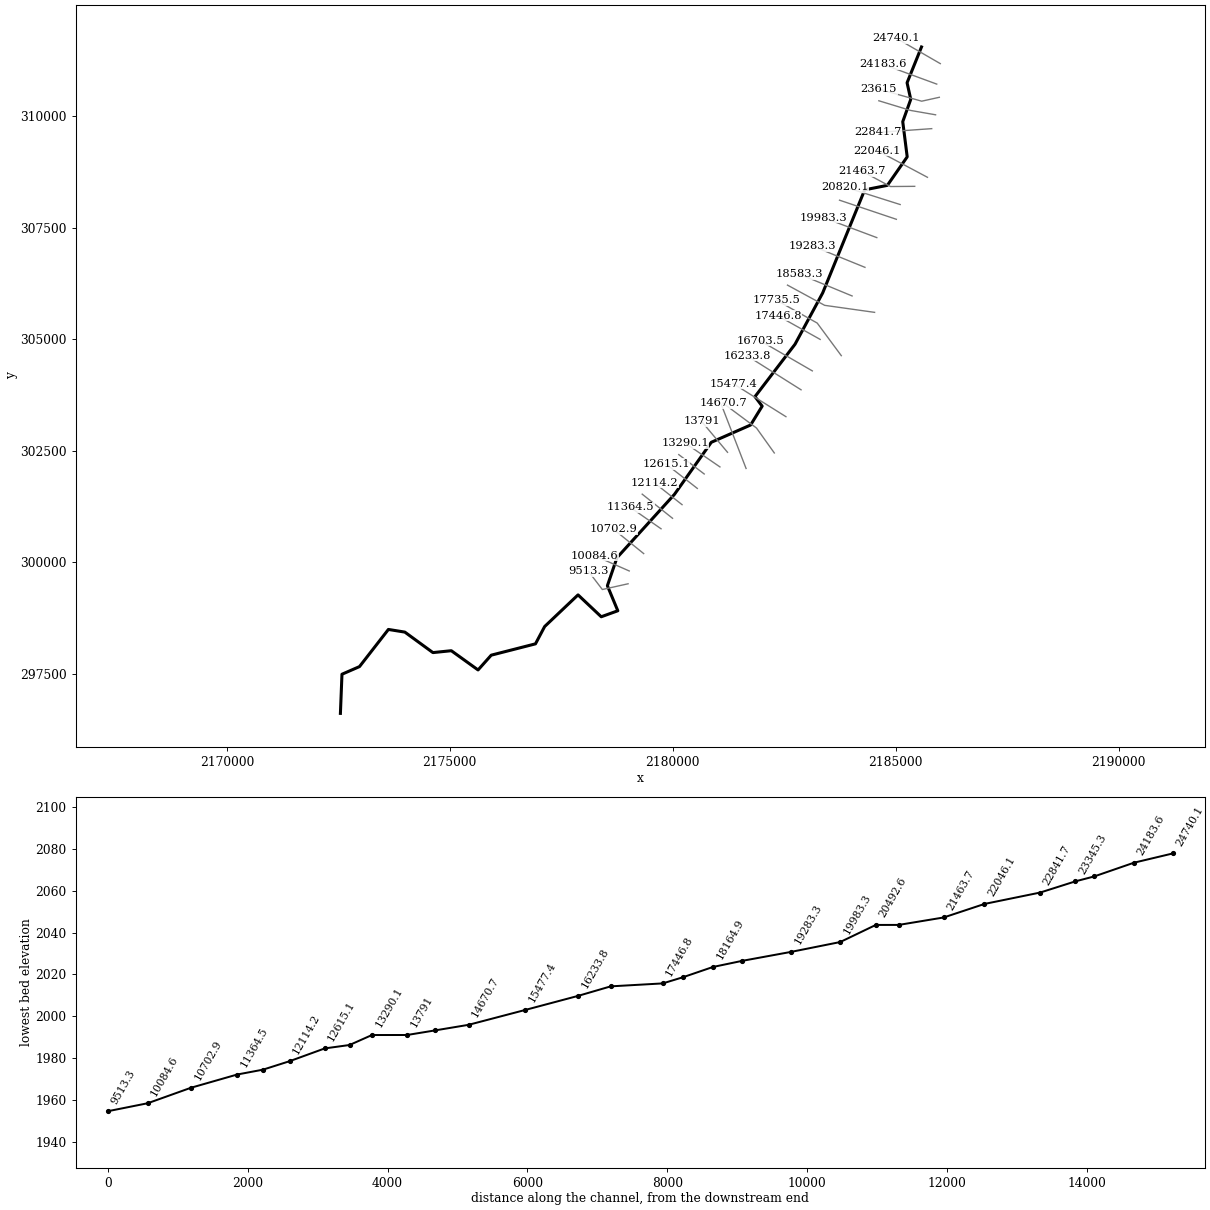
--- HowardCk.prj (project) ---

Proj Title=HowardCk
Current Plan=p01
Geom File=g01
Flow File=f01
Plan File=p01
DSS Export Rating Curves=0
DSS Export Rating Curve Sorted=0
DSS Export Volume Flow Curves=0
DXF OffsetX=0
DXF OffsetY=0
DXF ScaleX=0
DXF ScaleY=0

--- HowardCk.p01 (plan) ---

Plan Title=Floodplain
Program Version=4.00
Geom File=g01
Flow File=f01
K Sum by GR=0
Std Step Tol=0.01
Critical Tol=0.01
Num of Std Step Trials=20
Max Error Tol=0.3
Flow Tol Ratio=0.001
Split Flow NTrial=30
Split Flow Tol=0.02
Split Flow Ratio=0.02
Log Output Level=0
Friction Slope Method=1
Unsteady Friction Slope Method=2
Unsteady Bridges Friction Slope Method=1
Global Log Level=0
CheckData=False
Run HTab=0
Run UNet=0
Run PostProcess=0
UNET Theta=0
UNET Theta Warmup=0
UNET ZTol=0
UNET ZSATol=0
UNET MxIter=0
UNET MaxInSteps=0
UNET DtIC=0
UNET DtMin=0
UNET MaxCRTS=0
UNET WFStab=0
UNET SFStab=0
UNET WFX=0
UNET SFX=0
UNET DSS MLevel=0
UNET DZMax Abort=0
UNET Convert EG Bridges=0
UNET Use Existing IB Tables=0
UNET Froude Limit=0
UNET Froude Power=0
Write IC File=0
Echo Input=False
Echo Output=False
Write Detailed=0

--- HowardCk.f01 (steady flow) ---

Flow Title=NFF Regression Equation
Program Version=4.00
Number of Profiles=1
Profile Names=P100yr
River Rch & RM=HowardCk,Main      ,24740.1
1210.317
River Rch & RM=HowardCk,Main      ,22046.1
1263.541
River Rch & RM=HowardCk,Main      ,18164.9
1391.015
River Rch & RM=HowardCk,Main      ,17735.5
2195.631
River Rch & RM=HowardCk,Main      ,13290.1
2345.670
River Rch & RM=HowardCk,Main      ,2731.3
2597.495
River Rch & RM=HowardCk,Main      ,2476.9
4074.174
River Rch & RM=HowardCk,Main      ,201.9
4172.646
Boundary for River Rch & Prof#=HowardCk,Main      ,1
Up Type=0
Dn Type=3
Dn Slope=0.003339

--- HowardCk.g01 (geometry) ---

Geom Title=USGS 10m DEM
Program Version=4.10

River Reach=HowardCk        ,Main
Reach XY= 30
     2185580.289      311548.651     2185256.759      310746.157
      2185339.12      310374.294     2185159.675      309873.822
     2185259.433      309085.232     2184814.647       308446.26
     2184306.356      308346.292      2183364.12      306035.232
     2182743.807      304885.232      2181845.37      303710.232
     2182006.673      303496.988     2181747.571      303074.475
     2180865.682      302686.795      2180039.12      301519.607
     2178749.614      300099.546     2178535.038      299471.732
     2178768.807      298910.232     2178396.932      298775.857
      2177876.62      299266.482     2177128.182      298557.107
     2176921.772      298168.673     2175929.745      297914.919
     2175634.432      297583.669     2175034.432      298014.919
     2174621.932      297972.732     2173992.245      298432.107
     2173623.368      298491.696     2172975.058       297658.67
     2172582.036      297487.682     2172546.932      296610.232

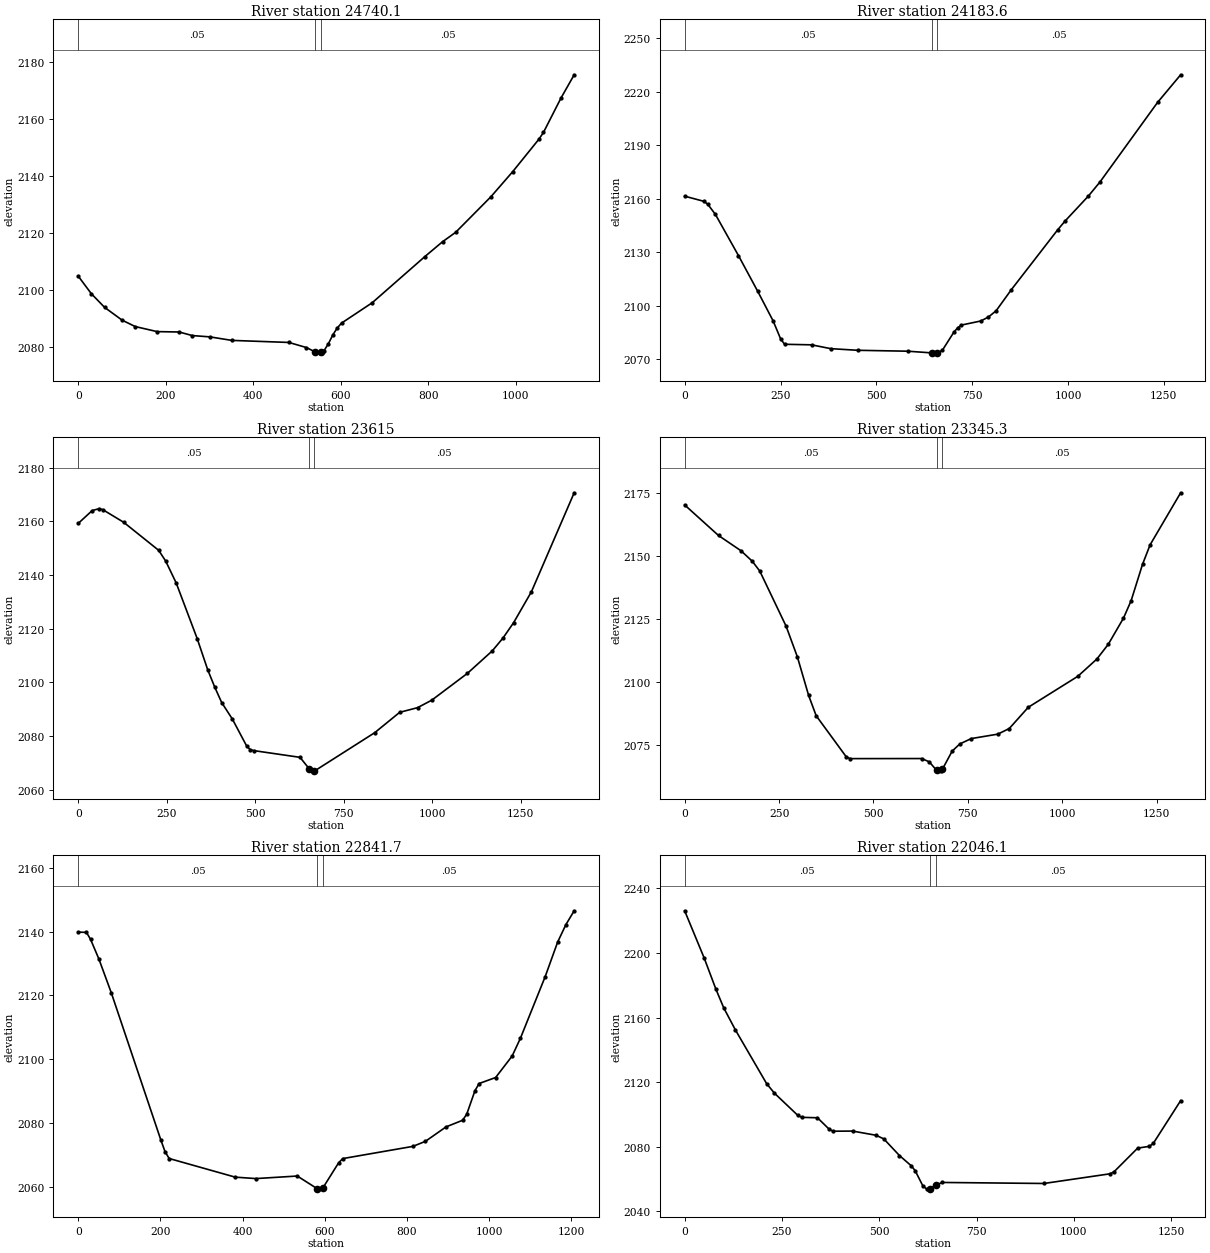
Type RM Length L Ch R = 1 ,24740.1 ,552.6,556.5,560.2
XS GIS Cut Line= 2
     2186001.811      311175.252     2185019.567      311742.024
#Sta/Elev= 30
       0 2104.91    30.1 2098.73    60.2 2093.98   100.4 2089.48   130.5 2087.24
   180.6 2085.47   230.8 2085.34   260.9 2084.09   301.1 2083.63   351.2  2082.4
   481.7 2081.68   521.9 2079.89   540.4 2078.47     552 2077.94   555.4 2078.23
     562 2078.79     572 2081.21   582.1  2084.3   592.1  2086.7   602.1 2088.45
   672.4  2095.6   792.8 2111.77     833 2116.94   863.1 2120.25   943.4 2132.66
   993.5 2141.49  1053.8 2152.93  1063.8 2155.22  1103.9 2167.27    1134  2175.4
#Mann= 3 , 0 , 0
       0     .05       0   540.4    .045       0   555.4     .05       0
Bank Sta=540.4,555.4
XS Rating Curve= 0 ,0
Exp/Cntr=0.3,0.1

Type RM Length L Ch R = 1 ,24183.6 ,567.2,568.6,570
XS GIS Cut Line= 2
     2185921.792       310716.22     2184707.381      311162.358
#Sta/Elev= 30
       0 2161.49    50.2  2158.6    60.2 2156.97    80.2 2151.26   140.4 2128.15
   190.6 2108.13   230.7 2091.58   250.7 2081.29   260.8 2078.46     331 2078.15
   381.1 2076.01   451.3 2075.09   581.7 2074.58   644.3 2073.64   651.9  2073.5
   659.3 2073.57     672 2075.01     702 2085.17   712.1 2087.68   722.1 2089.24
   772.2  2091.5   792.3 2093.73   812.4 2097.22   852.5 2109.16   972.8 2142.55
   992.9 2147.68  1053.1 2161.54  1083.2 2169.38  1233.6 2214.04  1293.8 2229.52
#Mann= 3 , 0 , 0
       0     .05       0   644.3    .045       0   659.3     .05       0
Bank Sta=644.3,659.3
XS Rating Curve= 0 ,0
Exp/Cntr=0.3,0.1

Type RM Length L Ch R = 1 ,23615   ,270,269.7,269.2
XS GIS Cut Line= 3
     2185980.099      310420.522     2185584.446      310333.062
      2184626.55      310603.772
#Sta/Elev= 30
       0 2159.25    39.5 2164.05    59.3 2164.76    69.2  2164.4   128.5 2159.67
   227.3 2149.22   247.1 2145.21   276.7 2137.06     336 2116.32   365.7 2104.71
   385.4 2098.29   405.2 2092.48   435.4 2086.31   475.6 2076.31   485.6 2074.95
   495.7 2074.57   626.4 2072.06   652.1 2067.83   666.6 2066.92   667.1 2066.95
   837.6 2081.27   907.9 2088.84   958.2 2090.57   998.4 2093.36    1099 2103.35
  1169.4 2111.75  1199.5 2116.51  1229.7 2122.27    1280 2133.81  1400.6 2170.66
#Mann= 3 , 0 , 0
       0     .05       0   652.1    .045       0   667.1     .05       0
Bank Sta=652.1,667.1
XS Rating Curve= 0 ,0
Exp/Cntr=0.3,0.1

Type RM Length L Ch R = 1 ,23345.3 ,495,503.6,512.2
XS GIS Cut Line= 3
     2185896.103      310028.073     2185337.366      310125.334
     2184623.424      310342.621
#Sta/Elev= 30
       0 2170.35    89.6 2158.21   149.2 2152.14   179.1 2147.97     199 2144.04
   268.6 2122.16   298.5 2109.94   328.3 2094.63   348.2 2086.59   427.8 2070.26
   437.8 2069.53   627.6 2069.56   647.8 2068.25   667.4 2064.83   678.1 2064.56
   682.4 2065.28   708.3 2072.49   728.5 2075.35   758.8 2077.49   829.3 2079.26
   859.6 2081.49     910 2089.94  1041.1 2102.24  1091.6 2109.11  1121.8 2114.96
  1162.1 2125.37  1182.3 2132.29  1212.6 2146.79  1232.7 2154.54  1313.4 2175.17
#Mann= 3 , 0 , 0
       0     .05       0   667.4    .045       0   682.4     .05       0
Bank Sta=667.4,682.4
XS Rating Curve= 0 ,0
Exp/Cntr=0.3,0.1

Type RM Length L Ch R = 1 ,22841.7 ,808.5,795.7,782.5
XS GIS Cut Line= 2
     2185809.188      309717.663       2184604.8      309632.818
#Sta/Elev= 30
       0 2139.86    20.1 2139.76    30.2 2137.54    50.3 2131.43    80.5 2120.82
   201.2 2074.61   211.3 2070.98   221.4 2068.81   382.3 2062.96   432.6 2062.51
   533.3 2063.31   581.2 2059.39   583.6  2059.2   596.2 2059.69   633.9 2067.44
   643.9 2068.78     815 2072.62   845.2 2074.19   895.5 2078.73   935.7  2080.8
   945.8 2082.69   965.9 2090.08     976 2092.34  1016.2 2094.22  1056.4 2100.96
  1076.6 2106.55  1136.9 2125.89  1167.1 2136.69  1187.2 2142.18  1207.4 2146.53
#Mann= 3 , 0 , 0
       0     .05       0   581.2    .045       0   596.2     .05       0
Bank Sta=581.2,596.2
XS Rating Curve= 0 ,0
Exp/Cntr=0.3,0.1

Type RM Length L Ch R = 1 ,22046.1 ,582.3,582.4,582.4
XS GIS Cut Line= 2
     2185713.701      308627.125      2184588.64      309225.794
#Sta/Elev= 30
       0 2226.12    50.2 2196.84    80.3 2177.56   100.4 2166.01   130.4 2152.32
   210.7 2119.04   230.8 2113.14     291 2099.36     301 2098.21   341.2 2097.95
   371.3 2090.86   381.3 2089.62   431.5 2089.71   491.7 2087.11   511.8 2084.85
   551.9 2074.55     582 2068.26   592.1 2065.26   612.1 2055.73   622.2 2053.75
   629.9 2054.08   644.9 2056.23   662.3 2057.88   923.2 2057.25  1093.8 2063.27
  1103.8 2064.62    1164 2079.14  1194.2 2080.26  1204.2 2082.09  1274.4 2108.53
#Mann= 3 , 0 , 0
       0     .05       0   629.9    .045       0   644.9     .05       0
Bank Sta=629.9,644.9
XS Rating Curve= 0 ,0
Exp/Cntr=0.3,0.1

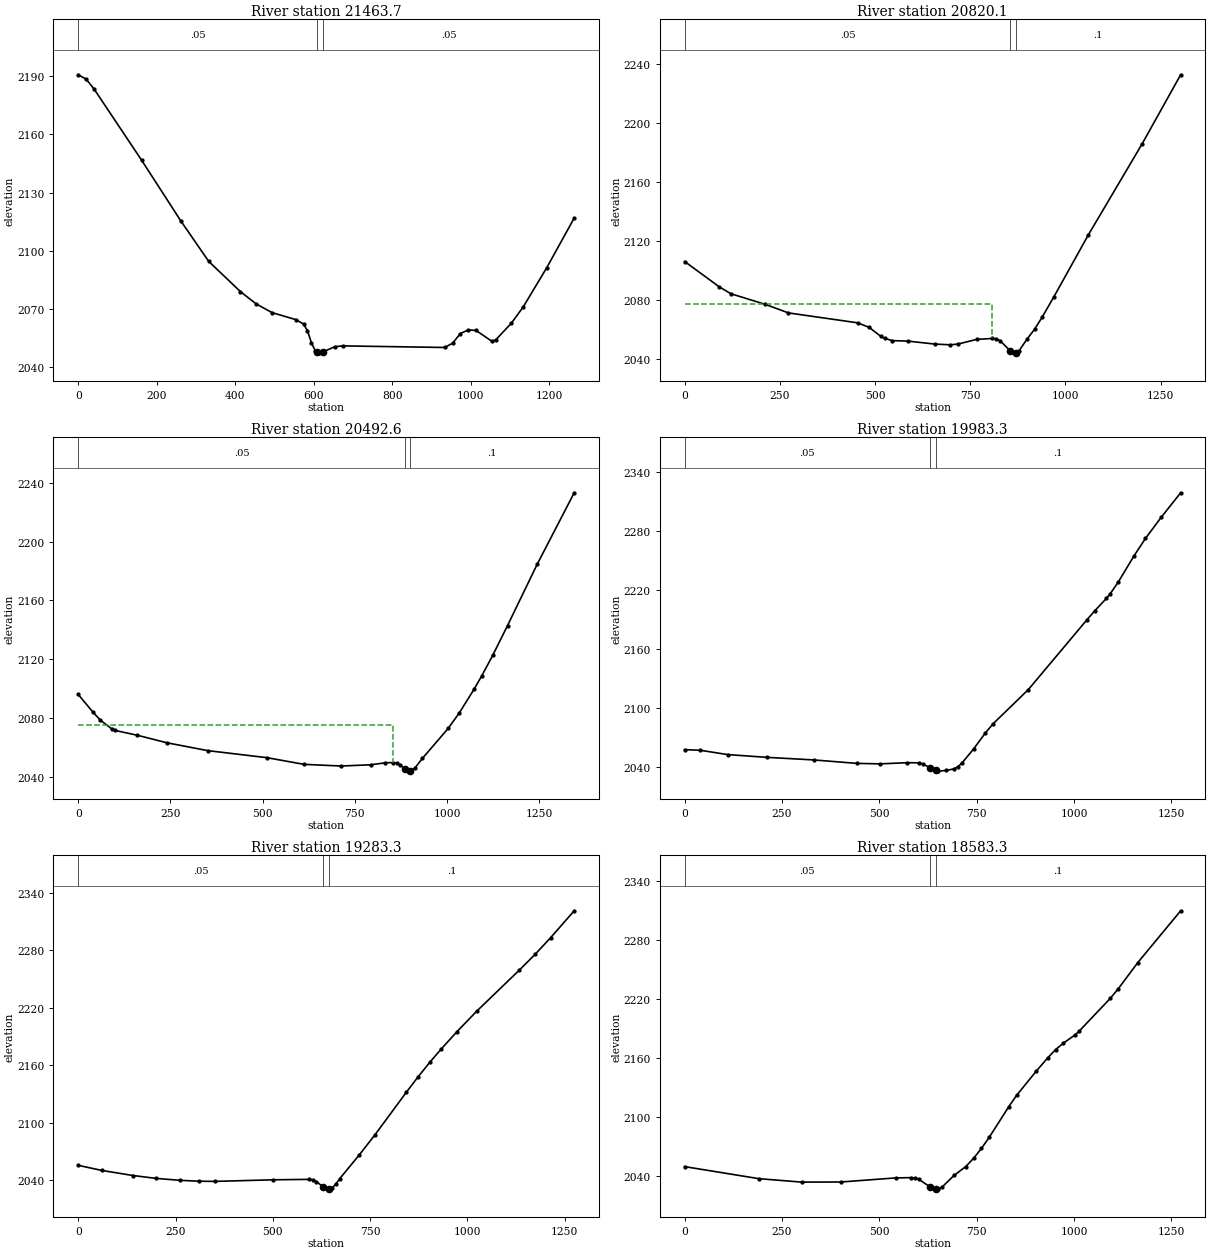
Type RM Length L Ch R = 1 ,21463.7 ,639.2,643.6,647.9
XS GIS Cut Line= 3
     2185428.419      308424.291     2184884.168      308420.152
     2184250.933      308761.603
#Sta/Elev= 30
       0 2190.66    20.2 2188.46    40.3 2183.37   161.3 2146.75     262 2115.22
   332.6 2094.53   413.2    2079   453.6 2072.61   493.9 2068.16   554.3 2064.55
   574.2 2062.27   584.2 2058.84   594.2 2052.59   604.2 2048.47     608 2048.02
   614.2 2047.28     623 2047.88   654.2 2050.61   674.2 2051.01     934 2050.19
   953.9 2052.39   973.9 2057.37   993.9 2059.24  1013.9 2058.96  1053.9  2053.4
  1063.8  2054.1  1103.8 2062.73  1133.8 2071.04  1193.8 2091.27  1263.7 2116.82
#Mann= 3 , 0 , 0
       0     .05       0     608    .045       0     623     .05       0
Bank Sta=608,623
XS Rating Curve= 0 ,0
Exp/Cntr=0.3,0.1

Type RM Length L Ch R = 1 ,20820.1 ,327.8,327.5,327
XS GIS Cut Line= 2
     2185101.455       308016.62     2183859.817      308409.805
#Sta/Elev= 30
       0 2105.99    90.9 2088.76   121.2 2084.11     212 2076.82   272.6 2071.05
   454.3 2064.31   484.6 2061.21   514.9 2055.15     525 2053.74   545.2  2052.2
   585.6 2051.89   656.2 2049.89   696.6 2049.37   716.8 2049.82   767.3 2053.08
   807.7 2053.66   817.8 2053.38   827.9 2052.26   855.1  2045.2   858.2 2044.45
   868.3 2043.71   870.1    2044   878.4 2045.35   898.6 2053.09   918.8 2059.93
   938.9 2068.22   969.2 2081.82  1060.1 2124.11  1201.4 2186.03  1302.4 2232.92
#Mann= 3 , 0 , 0
       0     .05       0   855.1    .045       0   870.1      .1       0
#XS Ineff= 2 , 0
          807.59 2076.78
Permanent Ineff=
       F       F
Bank Sta=855.1,870.1
XS Rating Curve= 0 ,0
Exp/Cntr=0.3,0.1

Type RM Length L Ch R = 1 ,20492.6 ,510,509.3,508.5
XS GIS Cut Line= 2
      2185016.61      307685.517     2183741.862      308113.882
#Sta/Elev= 30
       0 2095.92    40.1 2083.83    60.2 2078.37    90.3 2072.62   100.4 2071.38
   160.6 2068.11   240.9 2062.98   351.2 2057.66   511.8 2052.86   612.2 2048.32
   712.5 2047.18   792.8 2048.01     833 2049.37     853 2049.53   863.1 2049.15
   873.1 2047.84   885.2 2045.41   893.2  2043.7   900.2 2044.09   903.2 2044.08
   913.3 2045.93   933.3 2052.36  1003.6 2072.92  1033.7 2083.48  1073.8 2099.62
  1093.9  2108.4    1124 2122.54  1164.2 2142.84  1244.4 2184.46  1344.8  2233.2
#Mann= 3 , 0 , 0
       0     .05       0   885.2    .045       0   900.2      .1       0
#XS Ineff= 2 , 0
          854.28 2075.25
Permanent Ineff=
       F       F
Bank Sta=885.2,900.2
XS Rating Curve= 0 ,0
Exp/Cntr=0.3,0.1

Type RM Length L Ch R = 1 ,19983.3 ,700.6,700,699.4
XS GIS Cut Line= 2
     2184577.605      307275.116     2183384.421      307721.644
#Sta/Elev= 30
       0 2057.37    40.1 2056.72   110.4 2052.35   210.7 2049.54     331 2046.92
   441.4 2043.41   501.6 2042.89   571.8 2044.09   601.9 2043.95   611.9 2042.84
   629.5    2039   644.5 2036.17     652 2035.51   672.1  2036.2   692.2 2037.84
   702.2 2040.15   712.2 2043.72   742.3 2058.12   772.4 2074.38   792.5 2083.77
   882.8 2118.48  1033.2 2189.45  1053.3 2198.58  1083.4 2211.29  1093.4 2216.12
  1113.5 2227.68  1153.6  2254.1  1183.7 2272.28  1223.8 2293.61    1274 2318.68
#Mann= 3 , 0 , 0
       0     .05       0   629.5    .045       0   644.5      .1       0
Bank Sta=629.5,644.5
XS Rating Curve= 0 ,0
Exp/Cntr=0.3,0.1

Type RM Length L Ch R = 1 ,19283.3 ,700.1,700,699.8
XS GIS Cut Line= 2
      2184312.23      306608.712     2183131.725      307087.757
#Sta/Elev= 30
       0 2055.62    60.2 2050.34   140.4 2045.02   200.6 2041.99   260.8 2040.01
     311 2039.05   351.1 2038.88   501.6 2040.54   591.9 2040.98   601.9 2040.48
   611.9 2038.66   629.5 2033.07     632 2032.27     642 2030.81   644.5 2031.11
     652 2032.02   662.1 2036.25   672.1 2041.87   722.3 2066.65   762.4 2087.48
   842.6 2131.66   872.7  2147.7   902.8 2162.87   932.9 2177.12   973.1 2195.05
  1023.2 2216.18  1133.6 2259.35  1173.7 2275.66  1213.8 2293.13    1274 2321.02
#Mann= 3 , 0 , 0
       0     .05       0   629.5    .045       0   644.5      .1       0
Bank Sta=629.5,644.5
XS Rating Curve= 0 ,0
Exp/Cntr=0.3,0.1

Type RM Length L Ch R = 1 ,18583.3 ,420.6,418.4,416.1
XS GIS Cut Line= 2
     2184023.815      305967.226      2182846.48      306454.009
#Sta/Elev= 30
       0 2049.43   190.6 2037.16   300.9 2033.64   401.3 2033.78   541.7 2037.92
   581.8 2038.22   591.9 2037.85   601.9  2036.4   629.5 2029.01     642 2026.51
   644.5 2026.56     652 2026.69   662.1 2028.97   692.2 2040.56   722.3 2049.55
   742.3    2058   762.4 2067.99   782.5 2079.38   832.6 2110.49   852.7 2122.05
   902.8 2146.49   932.9 2160.35     953 2168.71   973.1 2175.25  1003.2 2183.68
  1013.2 2187.33  1093.4 2220.84  1113.5  2230.4  1163.6 2257.06    1274 2309.96
#Mann= 3 , 0 , 0
       0     .05       0   629.5    .045       0   644.5      .1       0
Bank Sta=629.5,644.5
XS Rating Curve= 0 ,0
Exp/Cntr=0.3,0.1

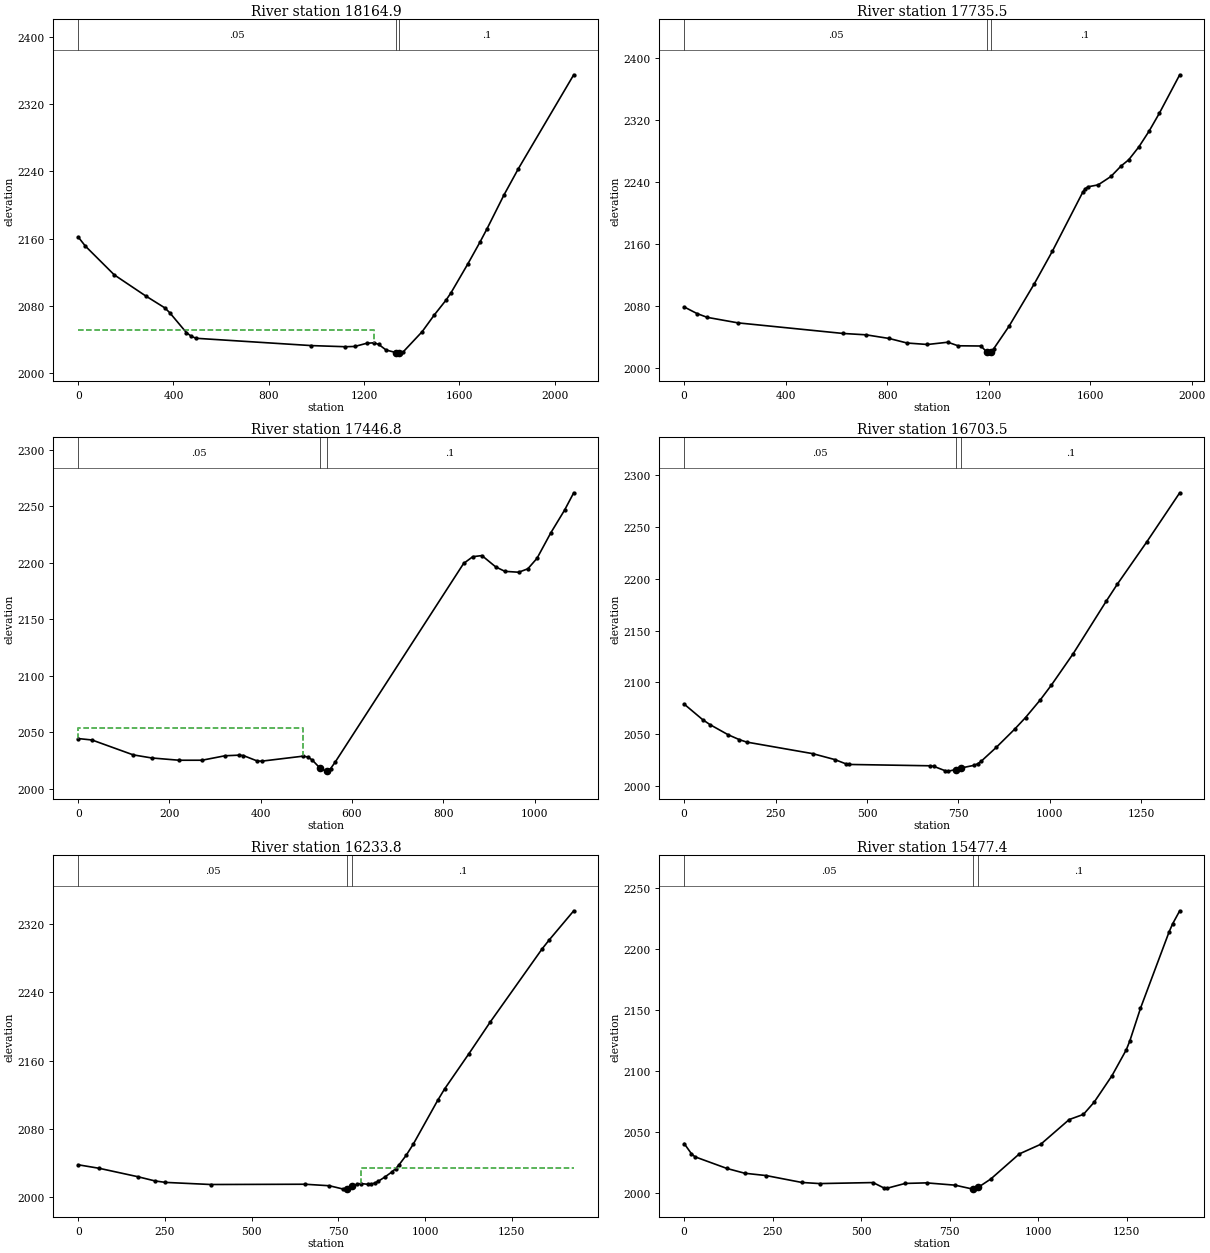
Type RM Length L Ch R = 1 ,18164.9 ,429.9,429.4,428.9
XS GIS Cut Line= 3
     2184528.232      305599.566     2183408.689       305756.84
     2182574.723      306210.038
#Sta/Elev= 30
       0 2161.91    30.3 2151.02   151.4 2116.81   282.6 2091.84   363.4 2077.53
   383.6 2071.92   454.2 2048.03   474.4 2043.68   494.6 2041.27   979.1 2032.55
  1120.4 2031.22  1160.8 2031.52  1211.3 2035.34  1241.6 2035.89  1261.8 2033.89
  1292.1  2027.3  1333.5 2024.23  1348.5 2023.63  1352.7 2023.58  1362.8 2024.68
  1443.6 2049.12    1494 2068.84  1544.5 2086.97  1564.7 2095.45  1635.4 2129.86
  1685.9 2155.58  1716.2 2171.87  1786.9  2211.9  1847.4 2243.25  2079.7 2355.08
#Mann= 3 , 0 , 0
       0     .05       0  1333.5    .045       0  1348.5      .1       0
#XS Ineff= 2 , 0
         1241.88 2050.94
Permanent Ineff=
       F       F
Bank Sta=1333.5,1348.5
XS Rating Curve= 0 ,0
Exp/Cntr=0.3,0.1

Type RM Length L Ch R = 1 ,17735.5 ,288.7,288.7,288.8
XS GIS Cut Line= 3
      2183781.18       304629.02     2183241.068      305359.517
     2182330.534      305870.657
#Sta/Elev= 30
       0 2078.31    50.5  2069.8    90.8 2064.88     212 2057.75   625.8 2044.08
   716.7 2042.31   807.5 2037.61   878.2 2031.73   958.7 2029.82    1039 2032.75
  1079.2 2028.16  1169.5 2027.86  1192.5 2020.12  1199.6 2018.66  1207.5 2019.76
  1219.7 2024.28    1280 2053.34  1380.4 2108.62  1450.7 2150.18  1571.2  2226.9
  1581.2 2231.22  1591.2 2233.54  1631.4 2236.05  1681.6 2246.88  1721.8 2260.46
  1751.9  2268.5    1792 2285.22  1832.2 2305.53  1872.4 2328.53  1952.7 2378.23
#Mann= 3 , 0 , 0
       0     .05       0  1192.5    .045       0  1207.5      .1       0
Bank Sta=1192.5,1207.5
XS Rating Curve= 0 ,0
Exp/Cntr=0.3,0.1

Type RM Length L Ch R = 1 ,17446.8 ,742.6,743.3,742.9
XS GIS Cut Line= 2
     2183307.289      304993.234     2182359.506      305522.999
#Sta/Elev= 30
       0 2044.53    30.2 2043.27   120.6 2030.09   160.9 2027.37   221.2 2025.34
   271.4 2025.36   321.7  2029.3   351.9 2029.83   361.9 2029.49   392.1 2024.73
   402.2 2024.54   492.6 2028.95   502.7 2028.26   512.7 2025.62   529.8 2018.41
   542.9 2015.71   544.8 2016.12     553 2017.91     563  2023.6   844.5 2199.45
   864.6 2205.47   884.7 2206.46   914.9 2196.44     935 2192.51   965.2 2191.72
   985.3 2194.76  1005.4 2204.04  1035.5  2226.5  1065.7 2246.62  1085.8 2261.99
#Mann= 3 , 0 , 0
       0     .05       0   529.8    .045       0   544.8      .1       0
#XS Ineff= 2 , 0
          493.66 2053.44
Permanent Ineff=
       F       F
Bank Sta=529.8,544.8
XS Rating Curve= 0 ,0
Exp/Cntr=0.3,0.1

Type RM Length L Ch R = 1 ,16703.5 ,471.2,469.7,468.7
XS GIS Cut Line= 2
      2183131.39       304287.57     2181958.043      304966.331
#Sta/Elev= 30
       0 2078.98    50.2  2064.1    70.3 2059.26   120.5 2049.37   150.6 2044.75
   170.7 2042.36   351.4 2031.19   411.7 2025.48   441.8 2021.42   451.8 2020.74
   672.7 2019.46   682.8 2018.91   712.9 2014.83     723  2014.3     743 2015.82
   746.3  2015.7     758 2017.38   793.2 2019.91   803.3 2021.45   813.3 2024.09
   853.5 2037.15   903.7 2054.67   933.8 2066.04     974 2083.02  1004.1 2097.15
  1064.3 2127.76  1154.7 2178.45  1184.8 2194.74  1265.2 2235.46  1355.5 2282.96
#Mann= 3 , 0 , 0
       0     .05       0     743    .045       0     758      .1       0
Bank Sta=743,758
XS Rating Curve= 0 ,0
Exp/Cntr=0.3,0.1

Type RM Length L Ch R = 1 ,16233.8 ,756.6,756.3,755.6
XS GIS Cut Line= 2
     2182878.924      303863.344     2181670.397      304624.881
#Sta/Elev= 30
       0 2038.15    60.4 2034.06     171  2024.3   221.3 2019.29   251.5 2017.58
   382.3 2015.11   653.9 2015.42   724.3 2013.65   764.5 2009.71   775.7 2010.13
   790.7 2013.01   804.8 2015.69   814.8 2016.24   834.9 2015.34     845 2015.49
   855.1 2016.92   865.1 2018.91   885.2 2024.17   905.4 2030.12   915.4  2033.8
   925.5 2038.44   945.6  2049.3   965.7 2062.11  1036.1 2113.28  1056.2 2126.76
  1126.7 2168.19    1187 2204.52  1337.9 2290.77    1358    2301  1428.4 2334.92
#Mann= 3 , 0 , 0
       0     .05       0   775.7    .045       0   790.7      .1       0
#XS Ineff= 2 , 0
                          816.22         2034.83
Permanent Ineff=
       F       F
Bank Sta=775.7,790.7
XS Rating Curve= 0 ,0
Exp/Cntr=0.3,0.1

Type RM Length L Ch R = 1 ,15477.4 ,810.8,806.8,809
XS GIS Cut Line= 2
     2182539.543      303261.149      2181353.78      304004.062
#Sta/Elev= 30
       0 2040.32    20.1 2032.15    30.2  2029.5   120.8 2019.91   171.1 2015.99
   231.5 2014.09   332.2 2008.44   382.5 2007.52   533.5 2008.35   563.7 2003.96
   573.8 2003.76   624.1 2007.64   684.5  2008.1   765.1 2006.21   815.4 2002.97
   815.8    2003   830.8 2004.54   865.7 2011.24   946.3 2031.83  1006.7 2039.71
  1087.2 2060.01  1127.5 2064.27  1157.7 2074.26    1208 2095.95  1248.3 2117.12
  1258.3 2124.36  1288.5  2151.2  1369.1  2213.7  1379.1 2220.37  1399.3 2231.18
#Mann= 3 , 0 , 0
       0     .05       0   815.8    .045       0   830.8      .1       0
Bank Sta=815.8,830.8
XS Rating Curve= 0 ,0
Exp/Cntr=0.3,0.1

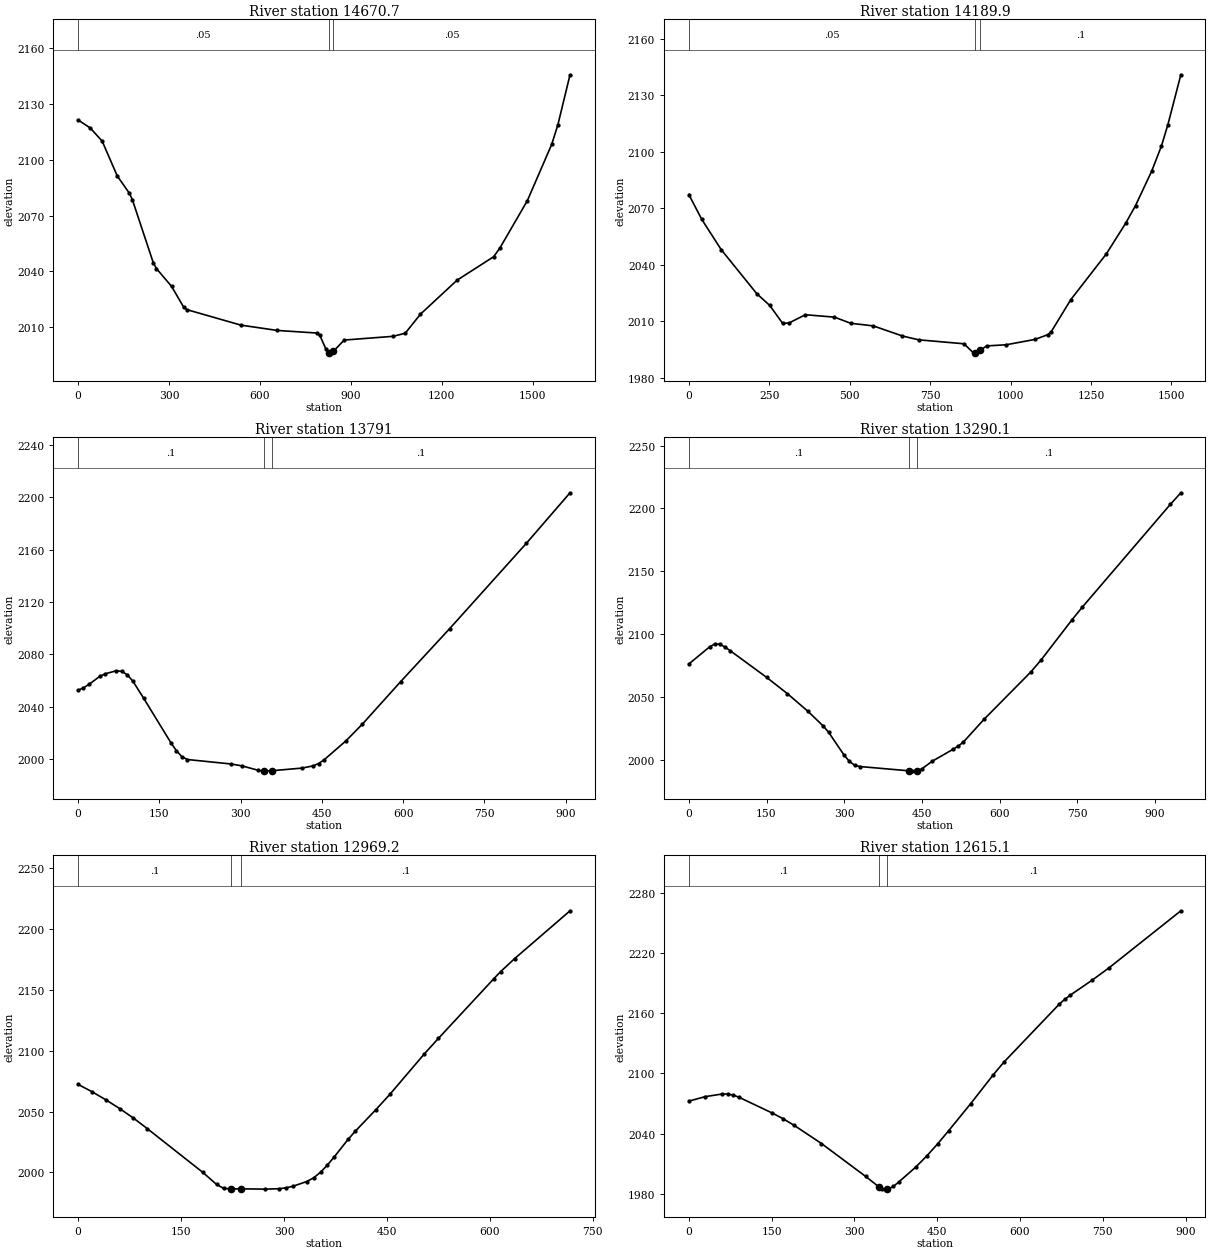
Type RM Length L Ch R = 1 ,14670.7 ,493.4,480.8,467.6
XS GIS Cut Line= 3
     2182278.799      302447.877     2181879.406      303006.614
     2181128.215      303565.351
#Sta/Elev= 30
       0 2121.51    39.8 2117.24    79.6 2110.12   129.4 2091.35   169.2 2082.05
   179.2 2078.58   248.8 2044.33   258.8 2041.42   308.6 2031.85   348.4 2020.69
   358.3 2019.34   537.5 2010.96   656.9 2008.11   787.5 2006.71   797.5 2005.56
   817.7 1998.08     827 1996.03   827.7 1995.88     842 1996.79   878.1 2002.92
  1039.1 2004.93  1079.4 2006.59  1129.7 2016.87  1250.5 2035.18  1371.3 2047.83
  1391.5 2052.44  1482.1 2077.94  1562.6 2108.31  1582.7 2118.67    1623  2145.8
#Mann= 3 , 0 , 0
       0     .05       0     827    .045       0     842     .05       0
Bank Sta=827,842
XS Rating Curve= 0 ,0
Exp/Cntr=0.3,0.1

Type RM Length L Ch R = 1 ,14189.9 ,391.3,398.8,406.3
XS GIS Cut Line= 2
     2181645.564      302100.219     2181093.036      303526.032
#Sta/Elev= 30
       0 2077.32    40.2 2064.14   100.6 2048.09   211.3 2024.71   251.5 2018.48
   291.7 2008.96   311.9 2009.23   362.2 2013.57   452.7 2012.28     503 2009.04
   573.4 2007.64     664 2002.28   714.3 2000.26   855.1 1998.16   885.3  1993.2
   890.5 1993.28   905.5 1994.66   925.5 1997.02   985.9 1997.62  1076.4 2000.49
  1116.7 2003.06  1126.7 2004.66  1187.1 2021.56  1297.8 2045.89  1358.1  2062.2
  1388.3 2071.46  1438.6 2089.73  1468.8 2103.03  1488.9 2114.37  1529.1 2140.82
#Mann= 3 , 0 , 0
       0     .05       0   890.5    .045       0   905.5      .1       0
Bank Sta=890.5,905.5
XS Rating Curve= 0 ,0
Exp/Cntr=0.3,0.1

Type RM Length L Ch R = 1 ,13791   ,494.3,500.9,507.4
XS GIS Cut Line= 2
     2181229.616      302462.363     2180646.046       303157.68
#Sta/Elev= 30
       0 2052.74    10.1 2054.52    20.2 2057.15    40.3 2063.34    50.4 2065.29
    70.6 2067.54    80.7 2067.12    90.8 2064.49   100.9 2059.81     121 2046.68
   171.5  2012.6   181.6 2006.56   191.6 2002.04   201.7 1999.87   282.4 1996.46
   302.6 1995.01   332.8 1991.61   342.9 1991.01   343.6 1991.01   358.6 1991.35
   413.5 1993.34   433.7 1995.01   443.8  1996.8   453.9 1999.58   494.2 2014.03
   524.5 2026.75   595.1 2059.18   685.9 2099.75   827.1 2164.69   907.8 2203.28
#Mann= 3 , 0 , 0
       0      .1       0   343.6    .045       0   358.6      .1       0
Bank Sta=343.6,358.6
XS Rating Curve= 0 ,0
Exp/Cntr=0.3,0.1

Type RM Length L Ch R = 1 ,13290.1 ,322,320.9,319.8
XS GIS Cut Line= 2
      2181059.58      302134.824     2180275.969      302671.947
#Sta/Elev= 30
       0 2076.25      40 2089.84      50  2092.2      60 2091.96      70  2089.7
      80  2086.8     150 2065.67     190 2052.76     230 2038.62     260 2026.69
     270 2021.89     300 2003.62     310 1998.78     320 1995.67     330 1994.67
   425.4 1991.23     430    1991   440.4  1991.3     450 1992.82     470 1998.89
     510 2008.33     520 2010.86     530 2014.06     570 2032.23     660 2069.74
     680 2079.36     740 2111.48     760 2121.61     930 2203.39     950 2212.47
#Mann= 3 , 0 , 0
       0      .1       0   425.4    .045       0   440.4      .1       0
Bank Sta=425.4,440.4
XS Rating Curve= 0 ,0
Exp/Cntr=0.3,0.1

Type RM Length L Ch R = 1 ,12969.2 ,354.4,354.1,353.8
XS GIS Cut Line= 2
     2180706.404       301976.63      2180136.17      302410.743
#Sta/Elev= 30
       0 2072.39    20.2 2066.39    40.4 2059.74    60.6 2052.52    80.8 2044.62
   100.9    2036   181.7 2000.04   201.9 1990.06     212 1986.88   222.8 1986.37
   237.8 1986.47   272.5 1986.22   292.7 1986.54   302.8 1987.28   312.9 1988.56
   333.1 1992.44   343.2  1995.5   353.3  2000.1   363.4 2006.12   373.5 2012.88
   393.7 2027.34   403.8  2033.8     434 2051.62   454.2 2064.12   504.7 2097.59
   524.9 2110.13   605.6 2159.21   615.7 2165.17   635.9 2175.75   716.7 2215.13
#Mann= 3 , 0 , 0
       0      .1       0   222.8    .045       0   237.8      .1       0
Bank Sta=222.8,237.8
XS Rating Curve= 0 ,0
Exp/Cntr=0.3,0.1

Type RM Length L Ch R = 1 ,12615.1 ,501,500.9,500.9
XS GIS Cut Line= 2
     2180551.889      301652.884     2179849.214      302201.044
#Sta/Elev= 30
       0 2072.31      30 2076.81    60.1 2079.37    70.1 2079.34    80.1 2078.36
    90.1 2076.33   150.2 2060.68   170.2 2054.92   190.3 2048.34   240.3 2030.04
   320.4 1997.21   343.8 1987.07   350.5 1984.76   358.8 1984.62   360.5 1984.59
   370.5 1987.26   380.5 1991.82   410.6 2006.31   430.6 2017.41   450.6 2029.64
   470.6 2042.77   510.7 2069.89   550.7 2098.03   570.8  2111.2   670.9  2168.9
   680.9 2173.75   690.9  2177.9     731 2193.03     761 2205.08   891.2 2261.98
#Mann= 3 , 0 , 0
       0      .1       0   343.8    .045       0   358.8      .1       0
Bank Sta=343.8,358.8
XS Rating Curve= 0 ,0
Exp/Cntr=0.3,0.1

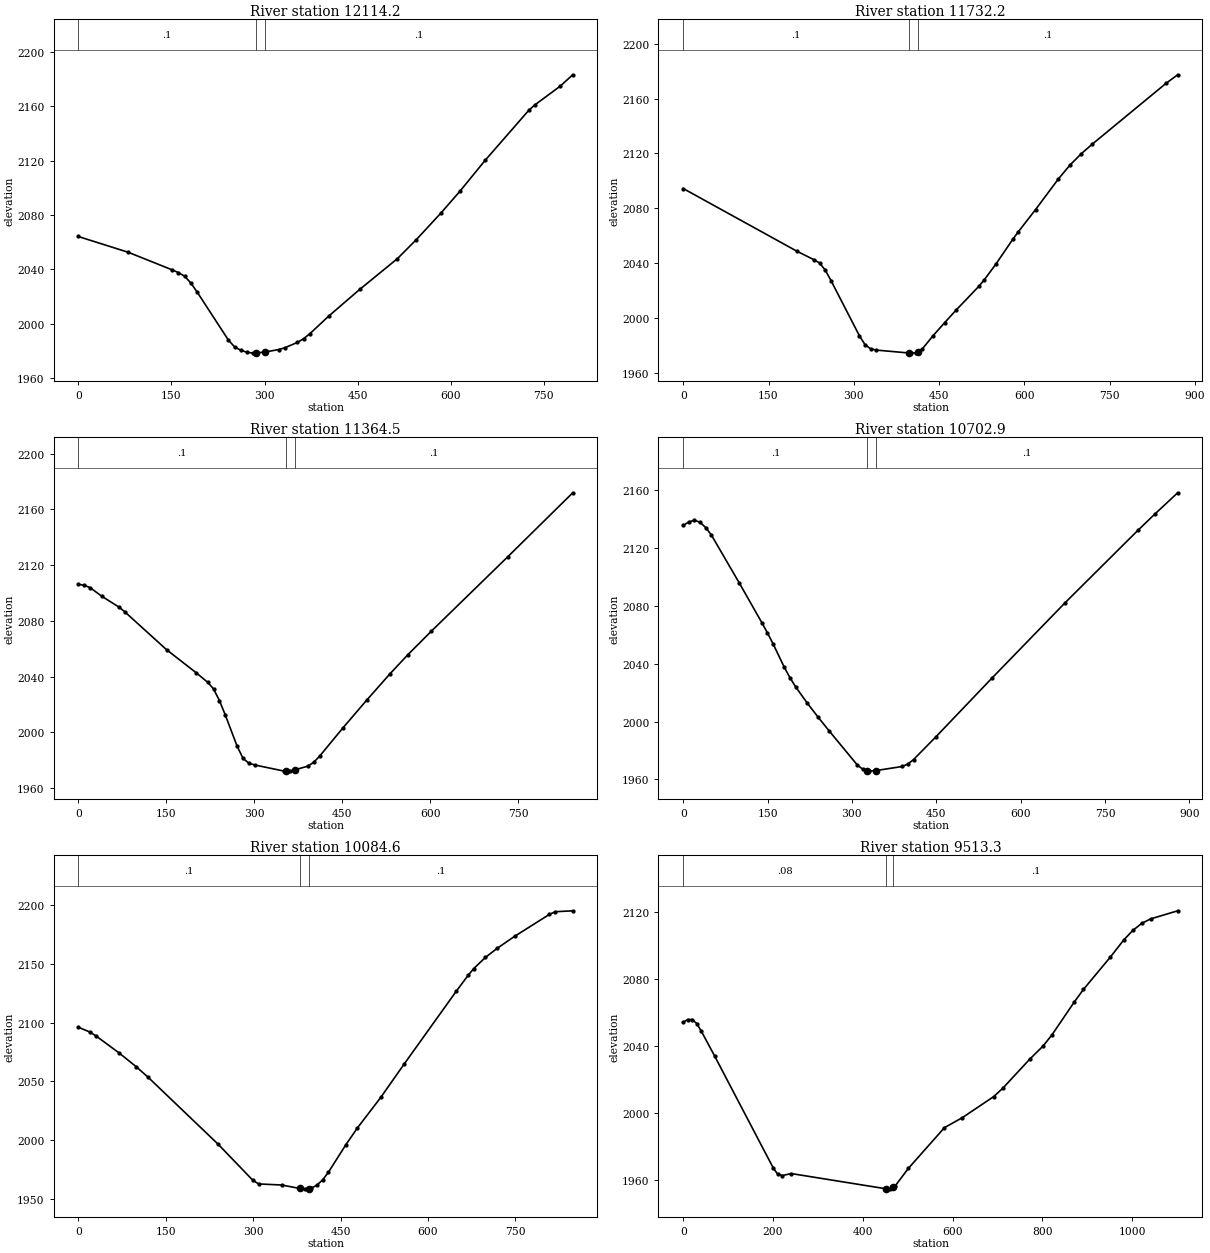
Type RM Length L Ch R = 1 ,12114.2 ,382,382,381.8
XS GIS Cut Line= 2
     2180209.749      301288.671     2179584.331      301781.647
#Sta/Elev= 30
       0 2064.22    80.6  2052.6   151.2  2039.7   161.3  2037.7   171.4 2035.02
   181.4 2029.99   191.5 2023.38   241.9 1988.04     252 1982.99   262.1 1980.54
   272.2 1979.08   282.2 1978.49   285.9 1978.57   300.9 1979.33   322.6 1981.07
   332.6  1982.4   352.8 1986.32   362.9 1989.06     373 1992.74   403.2 2005.62
   453.6 2025.42   514.1 2047.95   544.3  2061.8   584.7 2081.72   614.9 2097.54
   655.2 2120.09   725.8 2157.04   735.9 2161.08   776.2 2174.67   796.4 2183.04
#Mann= 3 , 0 , 0
       0      .1       0   285.9    .045       0   300.9      .1       0
Bank Sta=285.9,300.9
XS Rating Curve= 0 ,0
Exp/Cntr=0.3,0.1

Type RM Length L Ch R = 1 ,11732.2 ,366.4,367.7,369.1
XS GIS Cut Line= 2
     2179996.371       300983.32      2179315.77      301524.122
#Sta/Elev= 30
       0 2094.41   199.8 2048.73   229.8 2042.52   239.8  2040.1   249.8  2034.9
   259.8 2027.34   309.8 1987.08   319.7 1980.58   329.7 1977.51   339.7 1976.63
   397.1 1974.51   399.7 1974.42   409.7 1974.78   412.1 1975.35   419.7 1977.14
   439.6 1987.24   459.6 1996.59   479.6 2005.67   519.6 2023.04   529.6    2028
   549.6 2039.21   579.5 2057.41   589.5 2063.03   619.5 2079.04   659.5  2101.3
   679.4  2111.2   699.4 2119.59   719.4 2126.81   849.3  2171.2   869.3 2177.27
#Mann= 3 , 0 , 0
       0      .1       0   397.1    .045       0   412.1      .1       0
Bank Sta=397.1,412.1
XS Rating Curve= 0 ,0
Exp/Cntr=0.3,0.1

Type RM Length L Ch R = 1 ,11364.5 ,663.1,661.5,660
XS GIS Cut Line= 2
     2179738.846      300747.869     2179047.208      301229.808
#Sta/Elev= 30
       0 2106.21      10  2105.5    20.1 2103.81    40.1 2097.62    70.2 2089.61
    80.3 2086.07   150.5 2059.27   200.7 2042.81   220.8 2035.82   230.8    2031
   240.8 2022.64   250.9 2012.16     271 1989.83     281 1981.22     291 1977.76
   301.1  1976.5   351.2  1972.1   354.1 1972.13   361.3 1972.22   369.1 1972.99
   391.4 1975.67   401.4 1978.43   411.5 1982.83   451.6  2003.3   491.7    2023
   531.9 2042.14     562 2055.66   602.1 2072.58   732.6 2126.07     843 2171.84
#Mann= 3 , 0 , 0
       0      .1       0   354.1    .045       0   369.1      .1       0
Bank Sta=354.1,369.1
XS Rating Curve= 0 ,0
Exp/Cntr=0.3,0.1

Type RM Length L Ch R = 1 ,10702.9 ,612.4,618.3,624.2
XS GIS Cut Line= 2
      2179348.88      300192.351       2178664.6       300744.19
#Sta/Elev= 30
       0 2135.74      10  2138.2      20 2139.42      30 2137.94      40 2134.29
      50 2129.22    99.9 2095.84   139.8 2068.53   149.8 2061.44   159.8 2053.86
   179.8 2037.59   189.8 2030.44   199.8 2024.15   219.8 2013.24   239.8 2003.13
   259.7  1993.5   309.7 1969.96   319.7 1966.93   327.6    1966   329.6 1965.76
   342.6 1966.15   389.6 1968.97   399.6 1970.73   409.6 1973.76   449.5 1989.59
   549.4 2030.31   679.3  2082.4   809.1 2132.63   839.1 2143.84   879.1 2158.35
#Mann= 3 , 0 , 0
       0      .1       0   327.6    .045       0   342.6      .1       0
Bank Sta=327.6,342.6
XS Rating Curve= 0 ,0
Exp/Cntr=0.3,0.1

Type RM Length L Ch R = 1 ,10084.6 ,556.9,571.3,585.6
XS GIS Cut Line= 2
     2179025.135      299802.385     2178248.882      300144.525
#Sta/Elev= 30
       0 2096.18      20 2092.06    29.9 2088.92    69.9 2074.35    99.8  2062.4
   119.8  2053.6   239.5 1996.81   299.4 1965.94   309.4 1962.77   349.3 1961.85
   380.1 1958.89   389.2 1958.35   395.1 1958.73   399.2    1959   409.2 1961.66
   419.2 1966.18   429.1 1972.66   459.1 1996.13     479 2010.48     519 2036.43
   558.9 2064.66   648.7 2126.91   668.7 2140.22   678.6 2146.12   698.6 2155.61
   718.6 2163.29   748.5  2173.5   808.4 2192.23   818.4  2194.5   848.3 2195.25
#Mann= 3 , 0 , 0
       0      .1       0   380.1    .045       0   395.1      .1       0
Bank Sta=380.1,395.1
XS Rating Curve= 0 ,0
Exp/Cntr=0.3,0.1

Type RM Length L Ch R = 1 ,9513.3  ,807,780.4,753.7
XS GIS Cut Line= 3
     2178999.382      299515.429     2178421.791      299386.666
     2178112.761      299791.348
#Sta/Elev= 30
       0 2054.47      10 2055.89    20.1 2055.97    30.1 2053.56    40.1 2049.12
    70.2 2034.04   200.6 1967.14   210.6  1963.4   220.7 1962.64   240.7 1963.83
   452.2  1954.7   461.4 1954.52   467.2 1955.51   471.4 1956.22   501.5 1966.96
   581.7 1991.28   621.7 1997.29   691.6 2009.91   711.6 2014.85   771.5 2032.22
   801.4 2040.12   821.4  2046.9   871.3 2066.63   891.3 2073.99   951.2 2093.34
   981.1 2103.61  1001.1 2109.24  1021.1 2113.51    1041 2116.18    1101    2121
#Mann= 3 , 0 , 0
       0     .08       0   452.2    .045       0   467.2      .1       0
Bank Sta=452.2,467.2
XS Rating Curve= 0 ,0
Exp/Cntr=0.3,0.1