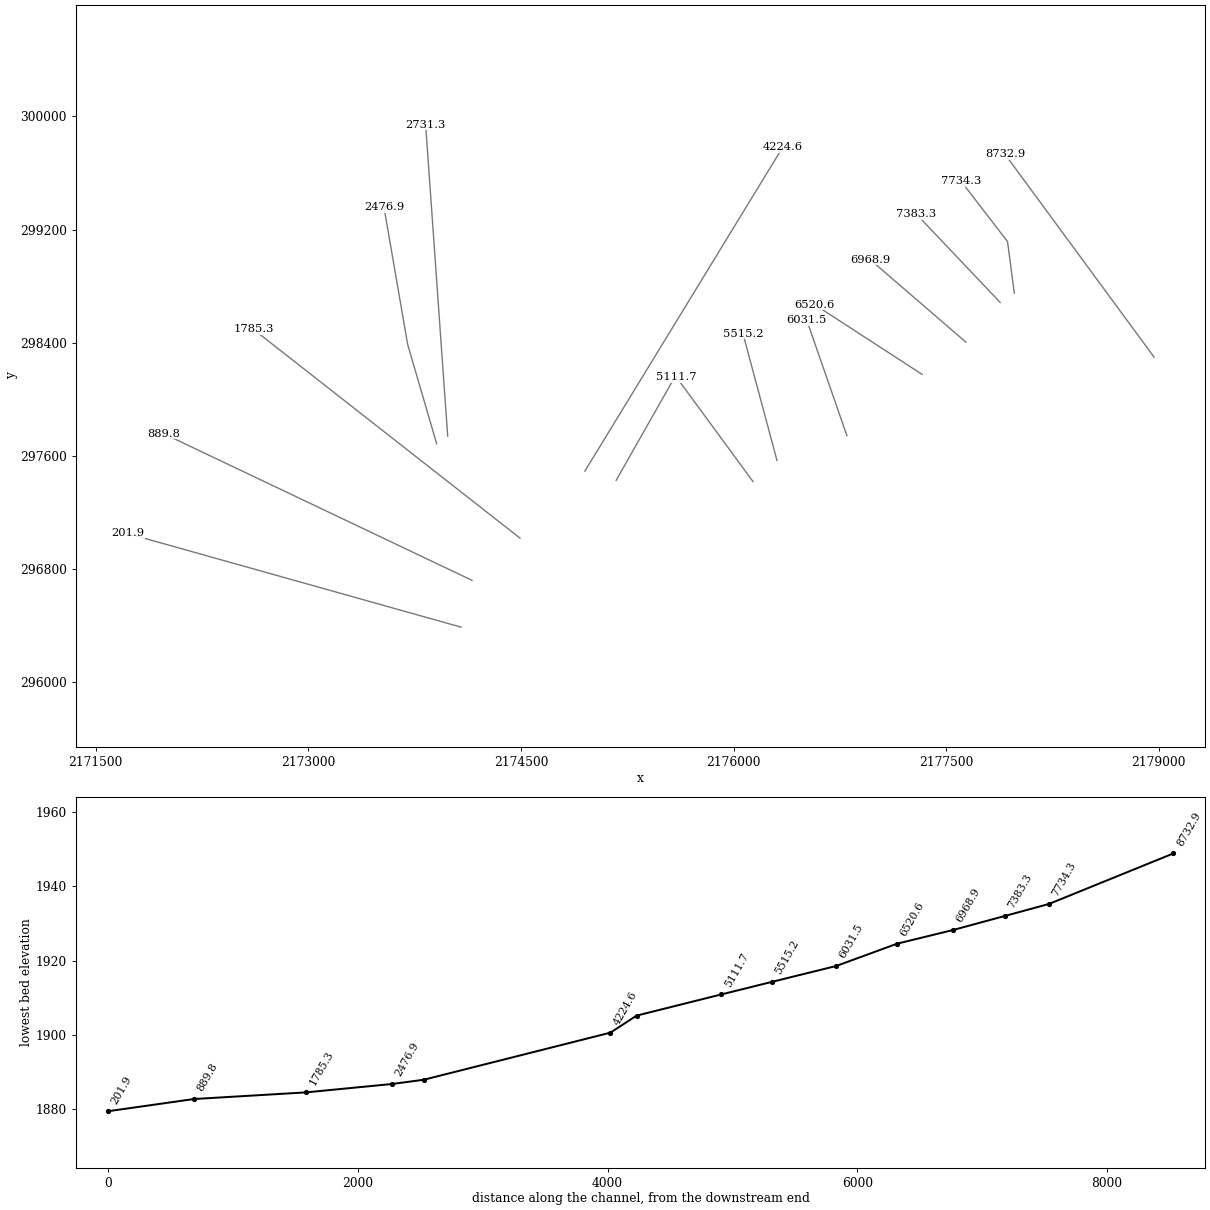
HEC-RAS study HowardCk.prj: HowardCk

--- HowardCk.g01 (geometry) --- (continued)

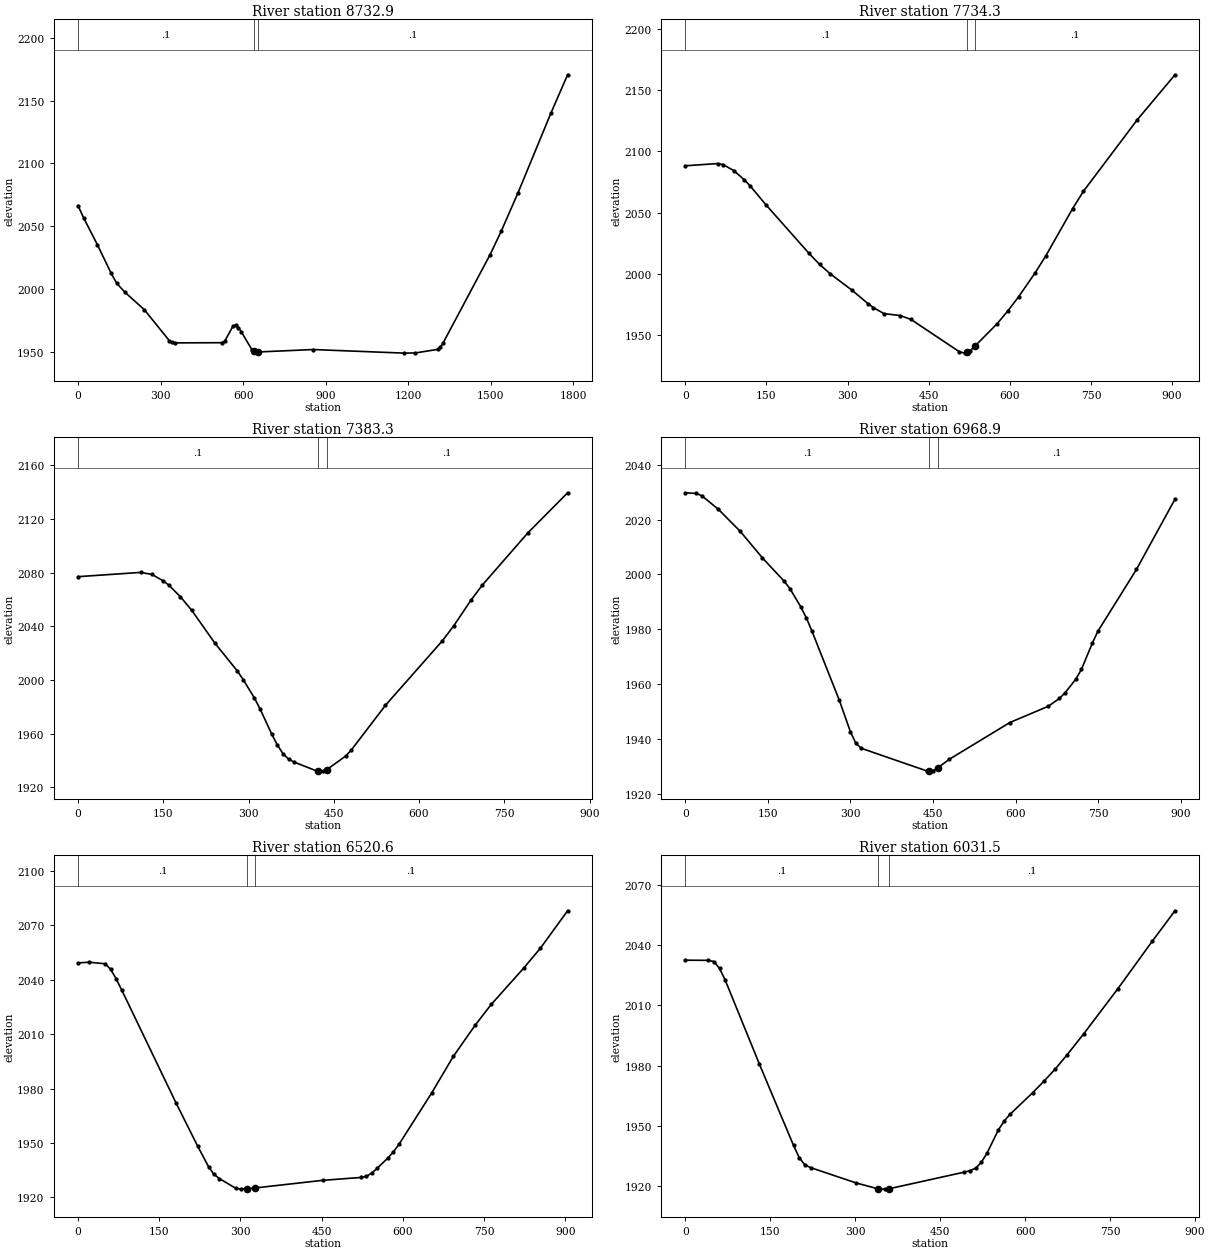
Type RM Length L Ch R = 1 ,8732.9  ,997.6,998.6,998.8
XS GIS Cut Line= 2
     2178966.272      298297.704     2177914.099      299732.485
#Sta/Elev= 30
       0 2066.31    20.1 2056.66    70.4 2035.13   120.6 2012.28   140.7 2004.38
   170.9 1997.19   241.2 1983.32   331.7 1958.75   341.8 1957.34   351.8 1956.94
   522.7 1957.08   532.8 1958.15   562.9 1970.17     573 1971.32     583 1969.16
   593.1 1965.92   633.3 1951.02   640.2 1950.12   655.2  1949.7   854.4 1951.64
  1186.2 1948.78  1226.4 1948.94  1306.8 1951.75  1316.8 1953.57  1326.9 1956.92
  1497.8 2027.31    1538 2045.87  1598.3 2076.09  1718.9  2140.1  1779.2 2170.46
#Mann= 3 , 0 , 0
       0      .1       0   640.2    .045       0   655.2      .1       0
Bank Sta=640.2,655.2
XS Rating Curve= 0 ,0
Exp/Cntr=0.3,0.1

Type RM Length L Ch R = 1 ,7734.3  ,348.6,351,353.3
XS GIS Cut Line= 3
      2177980.32      298750.212     2177932.494      299114.426
      2177605.07      299541.181
#Sta/Elev= 30
       0 2088.17    59.6 2089.98    69.5 2089.16    89.4 2084.28   109.2 2076.65
   119.1 2072.04   148.9 2056.34   228.4 2016.73   248.2 2007.58   268.1 1999.86
   307.8 1986.65   337.6 1975.61   347.5  1972.4   367.3 1967.42   397.2 1965.88
   417.2 1962.67   506.8 1936.24   516.8 1935.18   520.6 1935.95   526.7 1937.18
   535.6 1940.98   576.5 1959.22   596.4 1969.74   616.4 1981.36   646.2 2000.41
   666.2 2014.42     716 2053.18   735.9 2067.28   835.5 2125.72   905.2 2162.44
#Mann= 3 , 0 , 0
       0      .1       0   520.6    .045       0   535.6      .1       0
Bank Sta=520.6,535.6
XS Rating Curve= 0 ,0
Exp/Cntr=0.3,0.1

Type RM Length L Ch R = 1 ,7383.3  ,412.1,414.4,416.7
XS GIS Cut Line= 2
     2177880.989      298683.992     2177288.682      299309.409
#Sta/Elev= 30
       0 2076.96   110.2 2080.13   130.2  2078.6   150.2 2073.75   160.3 2070.43
   180.3 2061.92   200.3 2051.74   240.4 2027.62   280.4 2006.59   290.5 2000.28
   310.5 1986.42   320.5 1978.18   340.6 1959.76   350.6 1951.54   360.6 1945.05
   370.6 1940.88   380.6 1938.66   420.7 1931.98   422.5 1931.98   430.7 1931.98
   437.5 1933.04   470.8 1943.16   480.8 1947.67   540.9 1981.03     641 2029.09
   661.1 2040.31   691.1 2059.23   711.1 2070.56   791.3  2109.5   861.4 2139.46
#Mann= 3 , 0 , 0
       0      .1       0   422.5    .045       0   437.5      .1       0
Bank Sta=422.5,437.5
XS Rating Curve= 0 ,0
Exp/Cntr=0.3,0.1

Type RM Length L Ch R = 1 ,6968.9  ,445.4,448.3,450.7
XS GIS Cut Line= 2
      2177638.18      298404.393     2176964.937      298985.663
#Sta/Elev= 30
       0 2029.77      20 2029.55      30 2028.68      60 2023.75    99.9 2015.67
   139.9 2006.04   179.9 1997.44   189.9 1994.82   209.9 1988.09   219.9 1984.09
   229.9 1979.34   279.8 1954.02   299.8 1942.61   309.8 1938.35   319.8 1936.53
   439.7 1928.21   443.5 1928.24   449.7  1928.3   458.5 1929.39   479.7 1932.55
   589.6 1945.95   659.6  1951.9   679.6 1954.74   689.6 1956.71   709.6 1961.82
   719.6 1965.33   739.6    1975   749.5 1979.25   819.5 2001.79   889.5 2027.41
#Mann= 3 , 0 , 0
       0      .1       0   443.5    .045       0   458.5      .1       0
Bank Sta=443.5,458.5
XS Rating Curve= 0 ,0
Exp/Cntr=0.3,0.1

Type RM Length L Ch R = 1 ,6520.6  ,503.8,489,474.3
XS GIS Cut Line= 2
      2177329.15        298176.3     2176571.292      298669.276
#Sta/Elev= 30
       0 2049.27    20.1 2049.67    50.2 2048.81    60.3 2045.73    70.3  2040.6
    80.4 2034.52   180.8 1972.18     221 1948.21   241.1 1936.86   251.1 1932.67
   261.2 1930.34   291.3 1924.98   301.4 1924.53   311.4 1924.62   326.7 1925.17
     452 1929.39   522.4 1930.96   532.4 1931.56   542.4 1933.38   552.5 1936.02
   572.6  1941.8   582.6 1945.14   592.7 1949.23     653 1977.51   693.1 1997.73
   733.3  2014.9   763.4  2026.5   823.7 2046.64   853.9  2057.4   904.1 2078.01
#Mann= 3 , 0 , 0
       0      .1       0   311.4    .045       0   326.7      .1       0
Bank Sta=311.4,326.7
XS Rating Curve= 0 ,0
Exp/Cntr=0.3,0.1

Type RM Length L Ch R = 1 ,6031.5  ,517.9,516.3,514.7
XS GIS Cut Line= 2
     2176799.385      297742.187     2176516.108      298558.908
#Sta/Elev= 30
       0 2032.38    40.2 2032.29    50.3  2031.7    60.3  2028.3    70.4 2022.41
   130.7 1980.69     191 1940.24     201 1934.18   211.1 1930.56   221.1 1929.22
   301.6  1921.6   340.3 1918.66   351.8 1918.53  358.82 1918.66   492.5 1926.99
   502.6  1927.7   512.6 1928.98   522.7 1931.85   532.7 1936.49   552.8 1948.03
   562.9 1952.39     573 1955.67   613.2 1966.48   633.3 1972.25   653.4 1978.36
   673.5 1985.14   703.6 1995.85   763.9 2018.29   824.2 2041.74   864.4 2056.92
#Mann= 3 , 0 , 0
       0      .1       0   340.3    .045       0  358.82      .1       0
Bank Sta=340.3,358.82
XS Rating Curve= 0 ,0
Exp/Cntr=0.3,0.1

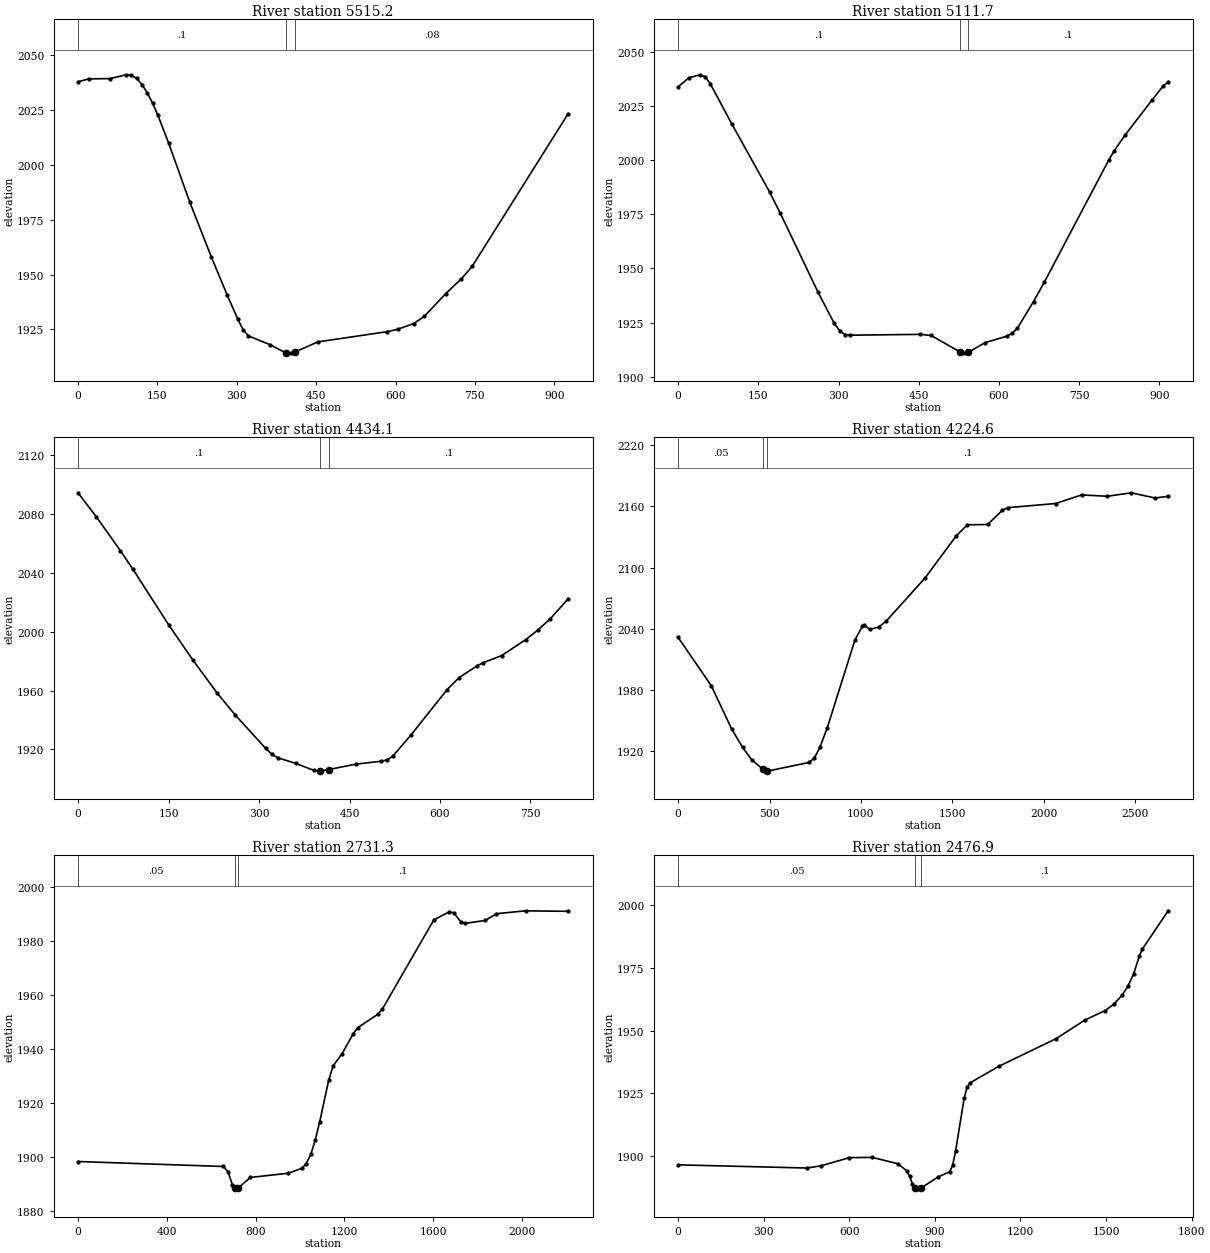
Type RM Length L Ch R = 1 ,5515.2  ,394.9,403.5,411.8
XS GIS Cut Line= 2
     2176305.893      297567.798     2176066.316      298462.333
#Sta/Elev= 30
       0 2037.68    20.1 2038.98    60.4 2039.12    90.6 2040.83   100.7 2040.63
   110.7  2039.2   120.8 2036.41   130.9 2032.64   140.9 2027.94     151 2022.41
   171.1 2009.84   211.4 1982.78   251.6 1958.19   281.8 1940.72     302 1929.65
     312  1924.9   322.1 1922.08   362.4 1918.13   392.6 1914.39   402.6 1914.25
   410.3 1914.78     453 1919.35   583.8 1923.99     604 1925.08   634.2  1927.7
   654.3 1930.93   694.6 1941.24   724.7 1948.09   744.9  1953.7   926.1 2023.08
#Mann= 3 , 0 , 0
       0      .1       0   392.6    .045       0   410.3     .08       0
Bank Sta=392.6,410.3
XS Rating Curve= 0 ,0
Exp/Cntr=0.3,0.1

Type RM Length L Ch R = 1 ,5111.7  ,705.4,677.7,648
XS GIS Cut Line= 2
     2176136.982      297417.847      2175595.78       298157.26
#Sta/Elev= 30
       0 2033.86    20.1 2037.99    40.3 2039.39    50.4  2038.6    60.4 2035.13
   100.7 2016.59   171.2 1985.23   191.3 1975.38   261.8 1938.94     292  1924.6
   302.1 1921.22   312.2 1919.44   322.2 1919.18   453.1 1919.55   473.3 1919.03
   527.7 1911.33   533.7 1910.89   542.7 1911.26     574 1915.73   614.2 1918.67
   624.3 1919.96   634.4 1922.39   664.6  1934.7   684.7  1943.6   805.6  2000.2
   815.6 2004.37   835.8 2011.56   886.1 2027.72   906.2 2034.03   916.3 2036.15
#Mann= 3 , 0 , 0
       0      .1       0   527.7    .045       0   542.7      .1       0
Bank Sta=527.7,542.7
XS Rating Curve= 0 ,0
Exp/Cntr=0.3,0.1

Type RM Length L Ch R = 1 ,4434.1  ,210.2,209.4,208.7
XS GIS Cut Line= 2
     2175171.494       297426.88     2175571.873      298133.673
#Sta/Elev= 30
       0 2094.45    30.1 2078.26    70.2 2055.13    90.3  2042.9   150.4 2004.58
   190.5 1980.65   230.7 1958.23   260.7 1943.33   310.9  1920.7   320.9 1916.79
   330.9  1914.3     361 1910.46   391.1 1905.65   400.5 1905.23   401.1  1905.2
   415.5 1906.27   461.3    1910   501.4 1911.87   511.5 1912.76   521.5 1915.21
   551.6 1929.63   611.8 1960.61   631.8 1968.84   661.9 1976.91   671.9 1978.99
     702 1983.72   742.1  1994.6   762.2 2001.13   782.2 2008.54   812.3 2022.27
#Mann= 3 , 0 , 0
       0      .1       0   400.5    .045       0   415.5      .1       0
Bank Sta=400.5,415.5
XS Rating Curve= 0 ,0
Exp/Cntr=0.3,0.1

Type RM Length L Ch R = 1 ,4224.6  ,1479.9,1493.3,1507.2
XS GIS Cut Line= 2
     2174950.876      297492.248     2176346.309      299781.209
#Sta/Elev= 30
       0 2031.61   181.4  1984.3   292.3 1942.13   352.7 1923.87   403.1 1911.64
   464.7 1902.37   483.8 1900.63  488.05 1900.63   715.6 1909.11   745.8 1913.49
     776 1924.14   816.3 1943.22   967.5 2029.11  1007.8  2042.5  1017.9 2043.58
  1048.1 2039.34  1098.5 2041.87  1138.8 2047.64  1350.5 2089.68  1521.8 2131.09
  1582.3 2141.84  1693.1 2142.17  1773.8 2156.04    1804 2158.66    2066 2162.72
  2207.1 2171.14  2348.2  2169.8  2479.2 2173.18  2610.2 2168.09  2680.8 2169.78
#Mann= 3 , 0 , 0
       0     .05       0   464.7    .045       0  488.05      .1       0
Bank Sta=464.7,488.05
XS Rating Curve= 0 ,0
Exp/Cntr=0.3,0.1

Type RM Length L Ch R = 1 ,2731.3  ,252,254.4,256.1
XS GIS Cut Line= 2
        2173983.      297738.843     2173827.391      299941.681
#Sta/Elev= 30
       0 1898.22   655.4 1896.38   675.6 1894.43   695.8 1889.55   705.1 1888.27
   715.9 1887.99  723.03 1888.49   776.4 1892.32   947.9 1893.88  1008.4 1895.69
  1028.5 1897.46  1048.7 1900.84  1068.9 1906.13    1089 1912.95  1129.4 1928.26
  1149.5 1933.67  1189.9 1938.19  1240.3  1945.6  1260.5 1947.82  1351.2 1952.83
  1371.4 1954.72  1603.3 1987.77  1673.9  1990.8  1694.1 1990.35  1724.3 1987.09
  1744.5 1986.48  1835.2 1987.56  1885.6 1990.07  2016.7 1991.13  2208.3 1990.95
#Mann= 3 , 0 , 0
       0     .05       0   705.1    .045       0  723.03      .1       0
Bank Sta=705.1,723.03
XS Rating Curve= 0 ,0
Exp/Cntr=0.3,0.1

Type RM Length L Ch R = 1 ,2476.9  ,674.6,691.6,708.6
XS GIS Cut Line= 3
     2173905.195      297685.352      2173700.71      298386.975
     2173533.204      299359.326
#Sta/Elev= 30
       0 1896.53   450.5 1895.26   500.6 1896.13   600.7 1899.41   680.8 1899.49
   771.1 1896.94   801.3 1894.13   811.4 1891.99   821.4 1888.82   829.8 1887.47
   841.6 1886.84   851.6 1887.29     912 1891.74   952.3 1893.78   962.4 1896.47
   972.4 1901.96  1002.6 1923.15  1012.7 1927.47  1022.8  1929.2  1123.5 1935.81
  1324.8 1946.87  1425.5 1954.28    1496 1958.05  1526.2 1960.51  1556.4 1964.25
  1576.5 1967.78  1596.7 1972.79  1616.8 1979.89  1626.9 1982.55  1717.5 1997.87
#Mann= 3 , 0 , 0
       0     .05       0   829.8    .045       0   851.6      .1       0
Bank Sta=829.8,851.6
XS Rating Curve= 0 ,0
Exp/Cntr=0.3,0.1

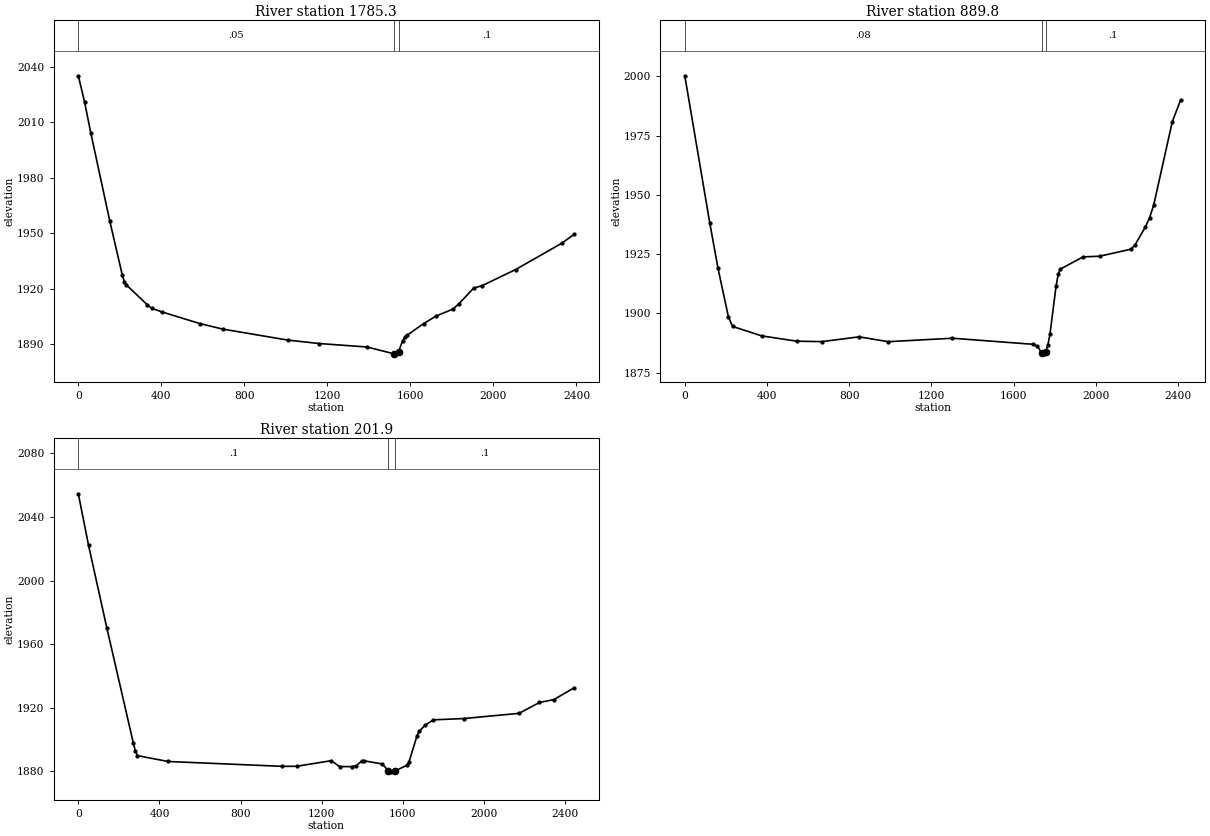
Type RM Length L Ch R = 1 ,1785.3  ,890.1,895.6,900.8
XS GIS Cut Line= 2
     2174493.299      297018.329     2172613.964      298493.198
#Sta/Elev= 30
       0 2035.25    30.2 2021.02    60.5 2004.09   151.2 1956.81   211.7 1927.46
   221.8  1923.8   231.8    1922   332.6 1911.26   352.8 1909.44   403.2 1907.41
   584.6 1901.15   695.5 1898.14    1008  1892.2  1159.2 1890.33    1391 1888.44
  1522.1 1884.72  1532.2 1884.58  1542.7 1885.77  1562.4  1891.8  1572.5 1893.69
  1582.6 1894.67  1663.2 1901.07  1723.7 1905.21  1804.3 1908.92  1834.6 1911.97
  1905.1 1920.34  1945.4 1921.64  2106.7 1930.36  2328.5 1944.55    2389 1949.42
#Mann= 3 , 0 , 0
       0     .05       0  1522.1    .045       0  1542.7      .1       0
Bank Sta=1522.1,1542.7
XS Rating Curve= 0 ,0
Exp/Cntr=0.3,0.1

Type RM Length L Ch R = 1 ,889.8   ,683.3,687.9,692
XS GIS Cut Line= 2
     2174154.202      296720.087     2171976.625      297757.806
#Sta/Elev= 30
       0 2000.24   121.1 1938.34   161.5 1919.04     212  1898.6   232.1  1894.5
   373.4 1890.51     545 1888.26   666.1 1888.07   847.8  1890.1   989.1 1888.05
    1302 1889.51  1695.6 1886.94  1715.8 1886.12    1736 1883.34  1746.1  1882.8
  1756.5 1883.87  1766.2 1886.63  1776.4  1891.1  1806.6 1911.73  1816.7  1916.5
  1826.8 1918.68  1937.8 1923.84  2018.6 1924.12    2170 1927.08  2190.2 1928.88
  2240.6 1936.42  2260.8 1940.28    2281 1945.61  2371.8 1980.92  2412.2 1990.03
#Mann= 3 , 0 , 0
       0     .08       0    1736    .045       0  1756.5      .1       0
Bank Sta=1736,1756.5
XS Rating Curve= 0 ,0
Exp/Cntr=0.3,0.1

Type RM Length L Ch R = 1 ,201.9   ,201.5,201.9,202.6
XS GIS Cut Line= 2
     2174076.577       296389.16     2171723.323      297051.013
#Sta/Elev= 30
       0  2054.5    50.3 2022.15   140.8 1970.01   271.6 1897.57   281.7 1892.69
   291.7 1889.88   442.6 1886.21    1006 1883.16  1076.4 1883.19  1247.4 1886.72
  1287.7    1883    1348 1882.98  1368.2 1883.48  1398.3  1886.6  1408.4 1886.65
  1498.9 1884.62  1529.1 1880.28  1539.2 1879.52  1559.3 1880.12  1619.6 1883.82
  1629.7 1885.75  1669.9  1902.4    1680 1905.13  1710.2 1909.08  1750.4 1912.39
  1901.3 1913.22  2172.9 1916.48  2273.5 1923.32    2344 1925.11  2444.6 1932.52
#Mann= 3 , 0 , 0
       0      .1       0  1529.1    .045       0  1559.3      .1       0
Bank Sta=1529.1,1559.3
XS Rating Curve= 0 ,0
Exp/Cntr=0.3,0.1

Chan Stop Cuts=-1
Use User Specified Reach Order=0
Composite Channel Slope=5